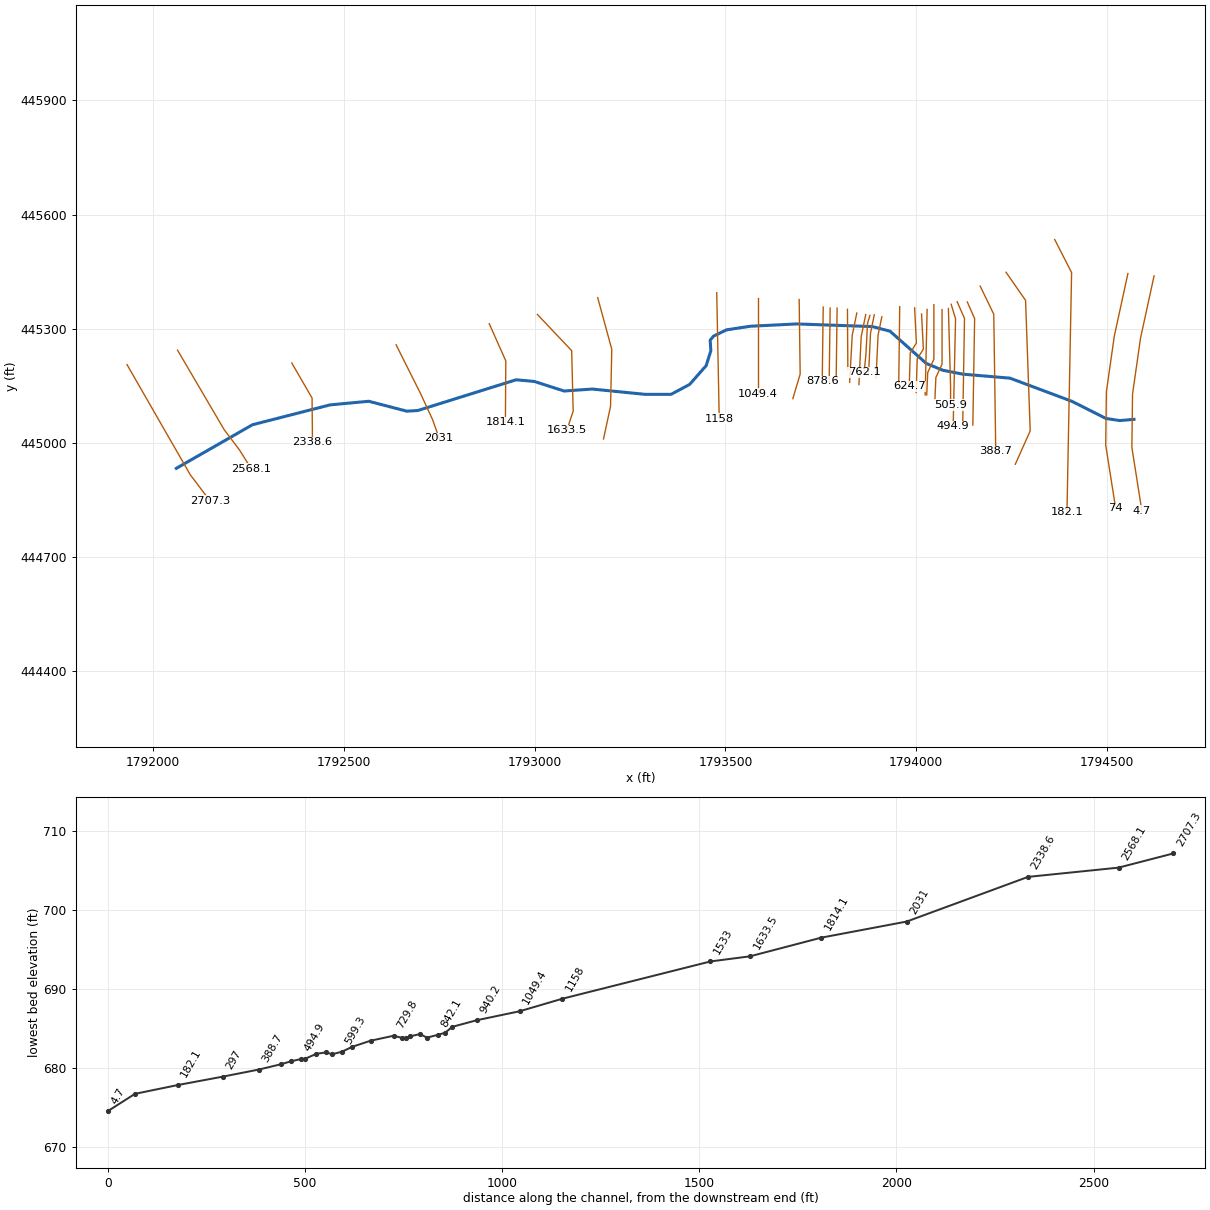
--- FOURMLEFK1.prj (project) ---

Proj Title=FOURMLEFK1
Current Plan=p01
Default Exp/Contr=0,0
English Units
Geom File=g01
Flow File=f01
Plan File=p01
BEGIN DESCRIPTION:
END DESCRIPTION:
DSS Export Rating Curves= 0
DSS Export Rating Curve Sorted= 0
DSS Export Volume Flow Curves= 0
DXF OffsetX= 0
DXF OffsetY= 0
DXF ScaleX= 0
DXF ScaleY= 0

--- FOURMLEFK1.p01 (plan) ---

Plan Title=Floodplain
Program Version=4.00
Geom File=g01
Flow File=f01
K Sum by GR=0
Std Step Tol=0.01
Critical Tol=0.01
Num of Std Step Trials=20
Max Error Tol=0.3
Flow Tol Ratio=0.001
Split Flow NTrial=30
Split Flow Tol=0.02
Split Flow Ratio=0.02
Log Output Level=0
Friction Slope Method=1
Unsteady Friction Slope Method=2
Unsteady Bridges Friction Slope Method=1
Global Log Level=0
CheckData=False
Run HTab=0
Run UNet=0
Run PostProcess=0
UNET Theta=0
UNET Theta Warmup=0
UNET ZTol=0
UNET ZSATol=0
UNET MxIter=0
UNET MaxInSteps=0
UNET DtIC=0
UNET DtMin=0
UNET MaxCRTS=0
UNET WFStab=0
UNET SFStab=0
UNET WFX=0
UNET SFX=0
UNET DSS MLevel=0
UNET DZMax Abort=0
UNET Convert EG Bridges=0
UNET Use Existing IB Tables=0
UNET Froude Limit=0
UNET Froude Power=0
Write IC File=0
Echo Input=False
Echo Output=False
Write Detailed=0

--- FOURMLEFK1.f01 (steady flow) ---

Flow Title=NFF Regression Equation
Program Version=4.10
Number of Profiles= 1
Profile Names=P100yr
River Rch & RM=FOURMLEFK1,Main            ,2707.3
848.6447
River Rch & RM=FOURMLEFK1,Main            ,2568.1
1279.573
River Rch & RM=FOURMLEFK1,Main            ,624.7
1331.588
Boundary for River Rch & Prof#=FOURMLEFK1,Main            , 1
Up Type= 0
Dn Type= 3
Dn Slope=0.009
DSS Import GetInterval= 0
DSS Import GetPeak= 0
DSS Import FillOption= 0

--- FOURMLEFK1.g01 (geometry) ---

Geom Title=USGS 10m DEM
Program Version=4.10

River Reach=FOURMLEFK1      ,Main
Reach XY= 30
     1792060.661      444933.318     1792260.314      445047.902
     1792463.439      445099.985     1792565.001      445109.534
     1792664.828      445083.492     1792693.474      445085.228
     1792951.286      445165.957     1792999.029      445161.617
     1793077.154      445136.443     1793150.939      445141.652
      1793288.96      445127.763     1793357.536      445127.763
     1793406.147      445153.804      1793449.55      445203.284
     1793461.703      445242.346     1793459.967      445270.124
     1793468.647      445280.541     1793502.501      445297.034
     1793565.001      445306.582     1793686.529      445312.659
     1793885.314      445305.714     1793931.321      445293.561
     1794026.309       445208.93     1794069.342      445191.131
     1794122.293      445180.714     1794245.557      445170.297
     1794407.883      445109.534     1794497.293      445064.395
     1794533.519      445058.792     1794570.808      445062.068

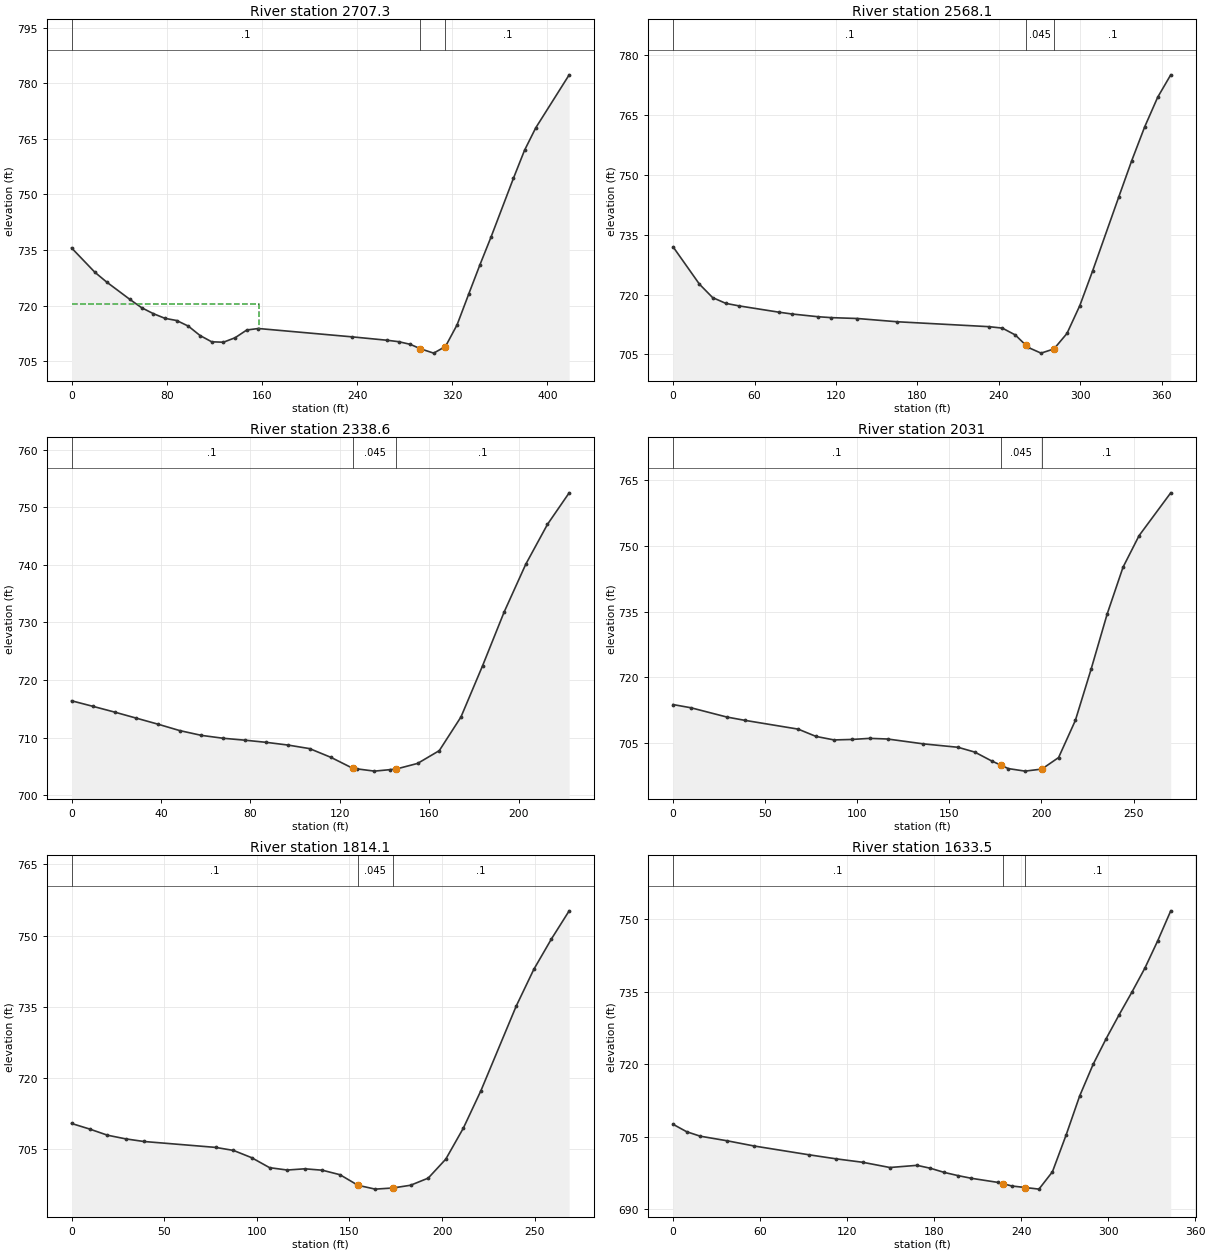
Type RM Length L Ch R = 1 ,2707.3  ,136.3,139.2,142
XS GIS Cut Line= 3
     1791931.451      445205.801     1792097.467      444916.087
     1792148.465      444848.813
#Sta/Elev= 30
       0  735.57    19.6  728.99    29.5  726.35    49.1  721.64    58.9  719.41
    68.8   717.8    78.6  716.53    88.4  715.95    98.2  714.43     108   711.9
   117.8   710.2   127.7  710.09   137.5   711.3   147.3  713.39   157.1  713.79
   235.7  711.54   265.2  710.62     275  710.23   284.8  709.51   293.3  708.31
   304.4  707.14   314.3  708.93   324.1   714.8   333.9  723.14   343.3  731.02
   352.7  738.57   371.4  754.34   380.8  761.96   390.2  768.01   418.3  782.33
#Mann= 3 , 0 , 0
       0      .1       0   293.3    .045       0   314.3      .1       0
#XS Ineff= 2 , 0
          157.22  720.54
Permanent Ineff=
       F       F
Bank Sta=293.3,314.3
XS Rating Curve= 0 ,0
Exp/Cntr=0.3,0.1

Type RM Length L Ch R = 1 ,2568.1  ,243.7,229.5,214.6
XS GIS Cut Line= 4
     1792063.829      445243.778     1792186.442       445034.36
      1792226.59      444981.192     1792256.972      444932.363
#Sta/Elev= 26
       0  731.98    19.4  722.63    29.1  719.27    38.8  717.82    48.5  717.19
    77.7  715.62    87.4  715.16   106.8  714.47   116.5  714.24   135.9  714.02
     165  713.21     233  711.97   242.7  711.61   252.2   709.9     260  707.33
   261.7  706.77   271.2  705.34   280.7  706.39   290.3  710.27   299.8  717.28
   309.3  726.03   328.5  744.51     338  753.56   347.6  762.08   357.2  769.52
   366.8  775.12
#Mann= 3 , 0 , 0
       0      .1       0     260    .045       0   280.7      .1       0
Bank Sta=260,280.7
XS Rating Curve= 0 ,0
Exp/Cntr=0.3,0.1

Type RM Length L Ch R = 1 ,2338.6  ,298.1,307.6,317.3
XS GIS Cut Line= 3
     1792363.309      445210.141     1792416.477       445117.91
     1792417.562      445001.808
#Sta/Elev= 26
       0  716.39     9.7  715.41    19.4  714.41      29  713.37    38.7  712.32
    48.4  711.21    58.1  710.38    67.8  709.88    77.4  709.55    87.1  709.17
    96.8   708.7   106.5  708.08   116.1  706.55   125.8  704.66   127.5  704.57
   135.5  704.17   142.5  704.43   145.2  704.53   154.8  705.51   164.5  707.73
   174.2  713.58   183.9  722.51   193.5   731.8   203.2  740.12   212.9  747.04
   222.6  752.51
#Mann= 3 , 0 , 0
       0      .1       0   125.8    .045       0   145.2      .1       0
Bank Sta=125.8,145.2
XS Rating Curve= 0 ,0
Exp/Cntr=0.3,0.1

Type RM Length L Ch R = 1 ,2031    ,226.6,216.8,206.7
XS GIS Cut Line= 4
     1792636.746      445257.884      1792701.85      445127.676
     1792732.232      445061.487     1792749.593      445012.659
#Sta/Elev= 25
       0  713.73     9.7     713    29.1  710.89    38.8  710.14    67.9  708.12
    77.6  706.45    87.4  705.65      97  705.76   106.8  706.01   116.5  705.86
   135.9  704.75   154.7  703.97   163.8  702.87   172.9  700.86   177.8  699.91
     182   699.1   191.1  698.52   200.2  698.99   209.3  701.62   218.4   710.1
     227  721.88   235.7  734.46   244.3  745.14     253  752.34   270.2  762.13
#Mann= 3 , 0 , 0
       0      .1       0   177.8    .045       0   200.2      .1       0
Bank Sta=177.8,200.2
XS Rating Curve= 0 ,0
Exp/Cntr=0.3,0.1

Type RM Length L Ch R = 1 ,1814.1  ,179.8,180.6,181.5
XS GIS Cut Line= 3
     1792880.887      445313.223      1792924.29      445215.567
     1792923.204      445053.891
#Sta/Elev= 25
       0  710.34     9.7  709.17    19.4  707.86    29.2  707.09    38.9  706.54
    77.7  705.29    87.4  704.65    97.2  703.12   106.9  701.01   116.4  700.51
   125.9  700.77   135.4  700.47   144.9  699.52   154.6  697.29   163.9  696.48
   173.4  696.72     183   697.3   192.5   698.8     202  702.81   211.5  709.37
     221  717.29     240   735.1   249.5  742.86     259  749.27   268.6  755.22
#Mann= 3 , 0 , 0
       0      .1       0   154.6    .045       0   173.4      .1       0
Bank Sta=154.6,173.4
XS Rating Curve= 0 ,0
Exp/Cntr=0.3,0.1

Type RM Length L Ch R = 1 ,1633.5  ,101.5,100.4,99.4
XS GIS Cut Line= 4
     1793007.102      445337.485     1793096.946      445242.433
     1793100.852      445083.579     1793083.925      445032.797
#Sta/Elev= 29
       0  707.55     9.3  706.02    18.7  705.09    37.4  704.13      56  703.05
    93.4  701.25   112.1  700.41   130.8  699.68   149.5   698.6   168.2  699.05
   177.5  698.44   186.9  697.59   196.2  696.94   205.6  696.37   224.3   695.5
   227.7  695.23   233.6  694.77     243  694.45   252.3  694.12   261.6  697.71
     271   705.3   280.4  713.44   289.7     720   298.6  725.27   307.5   730.2
   316.5  734.99   325.4  739.94   334.3  745.64   343.2  751.79
#Mann= 3 , 0 , 0
       0      .1       0   227.7    .045       0     243      .1       0
Bank Sta=227.7,243
XS Rating Curve= 0 ,0
Exp/Cntr=0.3,0.1

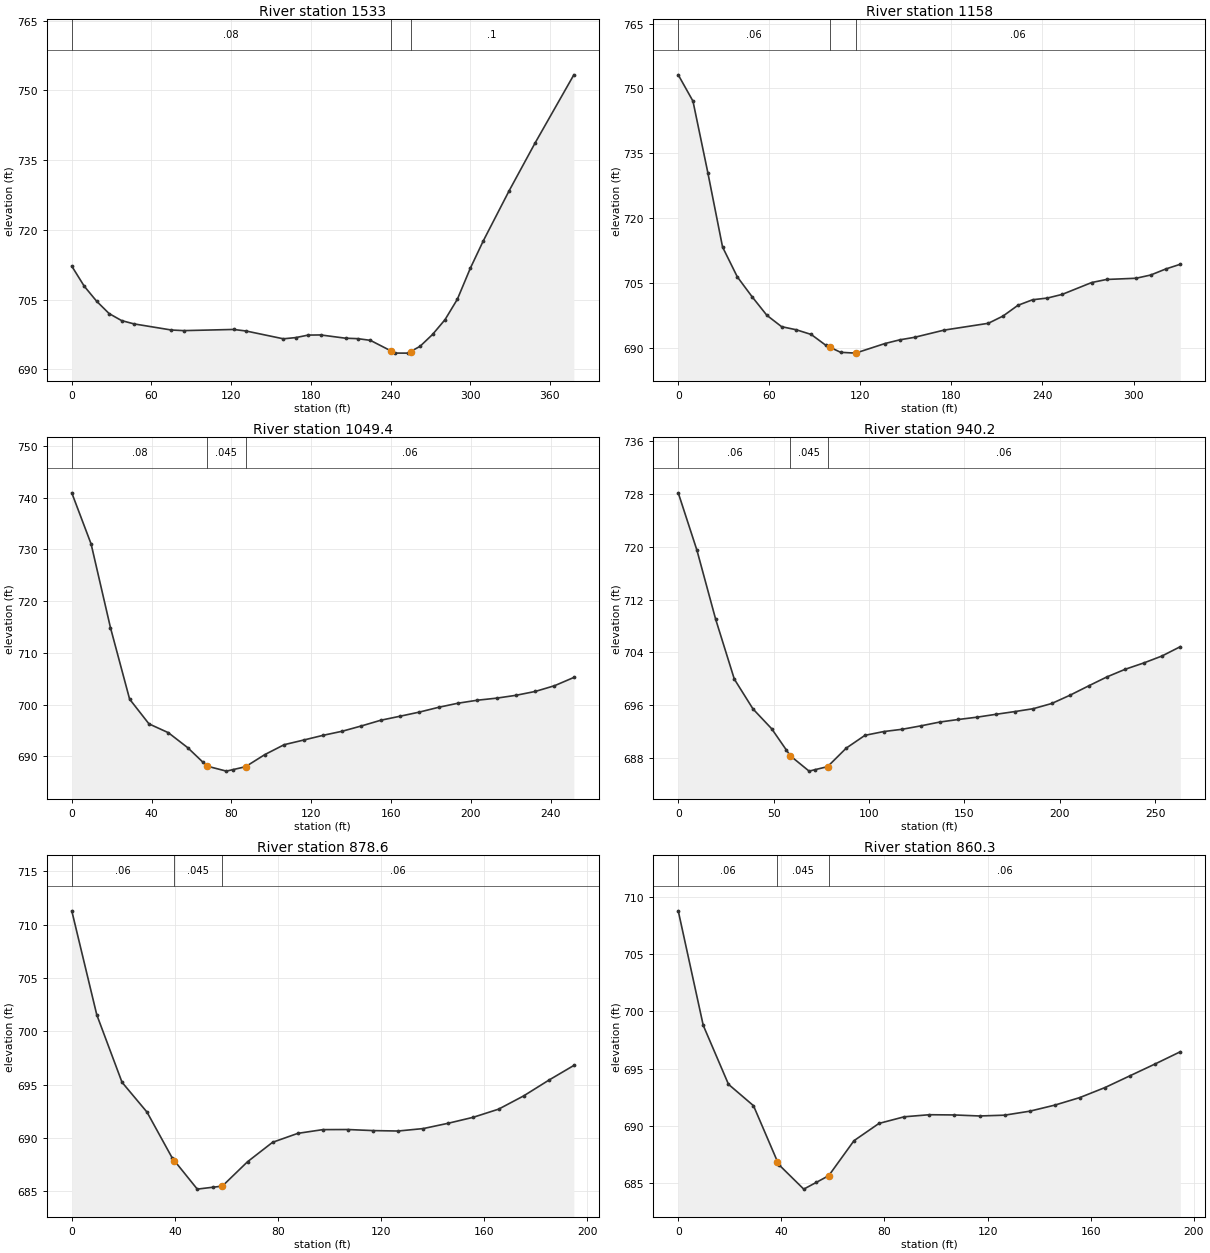
Type RM Length L Ch R = 1 ,1533    ,375.2,375.1,335.6
XS GIS Cut Line= 4
     1793165.175      445381.582     1793202.067      445245.948
     1793198.812      445096.209     1793180.366      445010.488
#Sta/Elev= 30
       0  712.18     9.4  707.86    18.7  704.64    28.1  701.98    37.5  700.47
    46.8  699.76      75  698.44    84.3  698.31   121.8  698.56   131.2  698.23
   159.3  696.55   168.6  696.81     178  697.35   187.4  697.38   206.1  696.68
   215.4  696.58   224.8  696.22   240.1  693.98   243.5  693.48   252.9  693.47
   255.1  693.82   262.2  694.93   271.6  697.48     281  700.66   290.3  705.06
   300.1  711.75   309.8   717.6   329.3   728.4   348.8  738.65     378  753.32
#Mann= 3 , 0 , 0
       0     .08       0   240.1    .045       0   255.1      .1       0
Bank Sta=240.1,255.1
XS Rating Curve= 0 ,0
Exp/Cntr=0.3,0.1

Type RM Length L Ch R = 1 ,1158    ,108.2,108.6,147.6
XS GIS Cut Line= 2
     1793477.154      445394.777     1793483.665      445064.047
#Sta/Elev= 30
       0  753.14     9.7  747.06    19.5  730.51    29.2  713.31    38.9  706.42
    48.6  701.83    58.4  697.51    68.1  694.88    77.8  694.16    87.6  693.08
    97.3  690.56    99.9  690.13     107  688.95   116.8  688.76   136.2  690.98
   145.9  691.83   155.7  692.42   175.1  694.08   204.3  695.66     214  697.34
   223.8  699.82   233.5  701.11   243.2   701.5     253  702.35   272.4  705.09
   282.2   705.8   301.6  706.08   311.3  706.83   321.1  708.21   330.8  709.32
#Mann= 3 , 0 , 0
       0     .06       0    99.9    .045       0   116.8     .06       0
Bank Sta=99.9,116.8
XS Rating Curve= 0 ,0
Exp/Cntr=0.3,0.1

Type RM Length L Ch R = 1 ,1049.4  ,108.8,109.2,109.4
XS GIS Cut Line= 2
     1793585.097      445380.497     1793585.097      445128.761
#Sta/Elev= 29
       0  740.94     9.7  731.05    19.4  714.89      29  701.08    38.7   696.3
    48.4   694.6    58.1  691.71    65.8  688.88    67.8  688.14    77.5  687.17
    80.8  687.46    87.1  688.02    96.8  690.37   106.5  692.28   116.2  693.17
   125.9  694.08   135.6  694.88   145.2   695.9   154.9     697   164.6  697.78
   174.3  698.58     184  699.51   193.6  700.29   203.3  700.87     213  701.27
   222.7  701.82   232.4  702.57     242  703.67   251.7  705.27
#Mann= 3 , 0 , 0
       0     .08       0    67.8    .045       0    87.1     .06       0
Bank Sta=67.8,87.1
XS Rating Curve= 0 ,0
Exp/Cntr=0.3,0.1

Type RM Length L Ch R = 1 ,940.2   ,62.2,61.6,61
XS GIS Cut Line= 3
     1793693.213      445376.721     1793695.817      445180.888
     1793676.547      445116.304
#Sta/Elev= 30
       0  728.16     9.8  719.47    19.6  709.04    29.4  699.96    39.2  695.44
      49  692.44    56.7  689.22    58.8  688.34    68.6  686.03    71.7  686.25
    78.3  686.71    88.1  689.52    97.9  691.45   107.7  692.02   117.5  692.37
   127.3  692.89   137.1  693.46   146.9  693.85   156.7   694.2   166.5  694.63
   176.3  695.04   186.1  695.48   195.8  696.27   205.5  697.54   215.1  698.93
   224.7  700.29   234.4  701.46     244   702.4   253.6  703.46   263.2  704.87
#Mann= 3 , 0 , 0
       0     .06       0    58.8    .045       0    78.3     .06       0
Bank Sta=58.8,78.3
XS Rating Curve= 0 ,0
Exp/Cntr=0.3,0.1

Type RM Length L Ch R = 1 ,878.6   ,18.3,18.3,18.3
XS GIS Cut Line= 2
     1793756.234      445356.929      1793753.63      445162.138
#Sta/Elev= 23
       0   711.3     9.7  701.55    19.5  695.22    29.2  692.42      39  688.11
    39.8  687.87    48.7   685.2    54.8  685.38    58.4  685.48    68.2  687.77
    77.9  689.59    87.7  690.43    97.4  690.78   107.1  690.79   116.9  690.69
   126.6  690.65   136.4  690.88   146.1  691.38   155.8  691.94   165.6   692.7
   175.3  693.94   185.1  695.42   194.8   696.8
#Mann= 3 , 0 , 0
       0     .06       0    39.8    .045       0    58.4     .06       0
Bank Sta=39.8,58.4
XS Rating Curve= 0 ,0
Exp/Cntr=0.3,0.1

Type RM Length L Ch R = 1 ,860.3   ,18.2,18.2,18.2
XS GIS Cut Line= 2
     1793774.463      445354.325     1793771.859      445159.534
#Sta/Elev= 23
       0   708.8     9.7  698.78    19.5  693.62    29.2  691.75    38.5  686.86
      39   686.6    48.7  684.45    53.5  685.03    58.4  685.63    68.2  688.69
    77.9   690.2    87.7  690.78    97.4  690.96   107.1  690.94   116.9  690.85
   126.6  690.92   136.4  691.27   146.1   691.8   155.8  692.46   165.6  693.34
   175.3  694.37   185.1  695.41   194.8  696.47
#Mann= 3 , 0 , 0
       0     .06       0    38.5    .045       0    58.4     .06       0
Bank Sta=38.5,58.4
XS Rating Curve= 0 ,0
Exp/Cntr=0.3,0.1

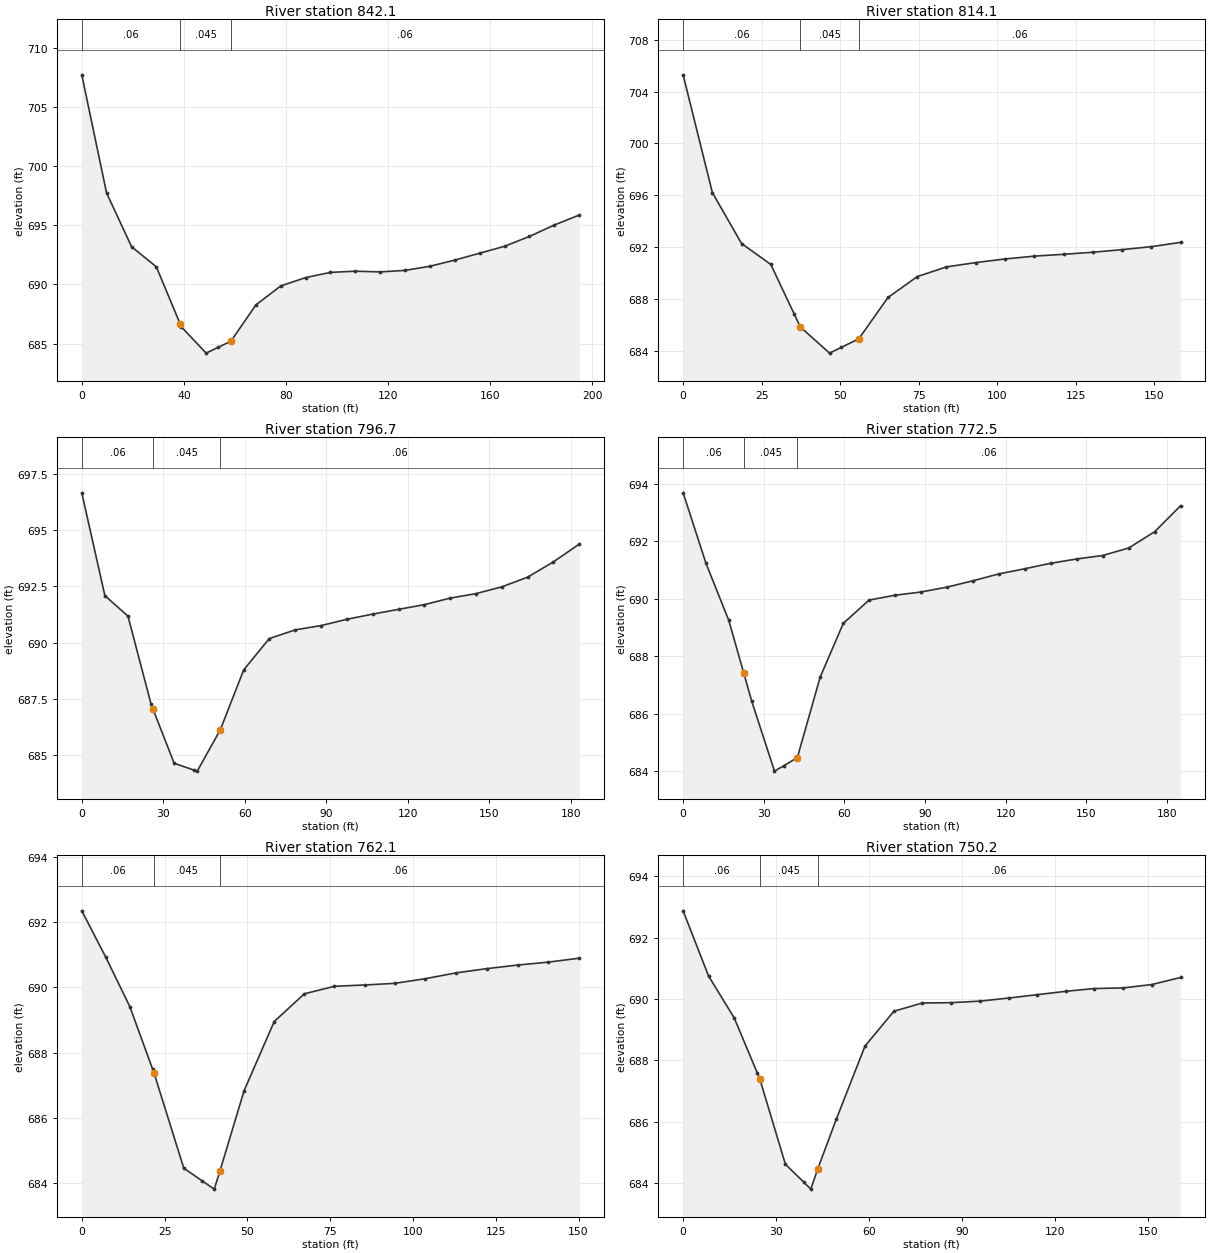
Type RM Length L Ch R = 1 ,842.1   ,27.5,28,28.4
XS GIS Cut Line= 2
     1793792.692      445354.325     1793790.088      445159.534
#Sta/Elev= 23
       0  707.73     9.7  697.74    19.5  693.19    29.2  691.49    38.5  686.67
      39  686.41    48.7  684.19    53.5  684.69    58.4   685.2    68.2  688.27
    77.9  689.87    87.7  690.58    97.4  691.02   107.1  691.12   116.9  691.06
   126.6  691.19   136.4  691.54   146.1  692.06   155.8  692.64   165.6  693.23
   175.3  694.06   185.1  695.03   194.8  695.87
#Mann= 3 , 0 , 0
       0     .06       0    38.5    .045       0    58.4     .06       0
Bank Sta=38.5,58.4
XS Rating Curve= 0 ,0
Exp/Cntr=0.3,0.1

Type RM Length L Ch R = 1 ,814.1   ,22,17.4,12.5
XS GIS Cut Line= 2
     1793819.776        445351.2     1793820.817      445192.867
#Sta/Elev= 20
       0  705.29     9.3  696.21    18.6  692.28    27.9  690.67    35.4  686.82
    37.3  685.85    46.6  683.83    50.4  684.28    55.9  684.93    65.2  688.12
    74.5  689.73    83.8  690.48    93.1  690.81   102.4  691.09   111.8  691.31
   121.1  691.45   130.4  691.61   139.7  691.81     149  692.04   158.3  692.37
#Mann= 3 , 0 , 0
       0     .06       0    37.3    .045       0    55.9     .06       0
Bank Sta=37.3,55.9
XS Rating Curve= 0 ,0
Exp/Cntr=0.3,0.1

Type RM Length L Ch R = 1 ,796.7   ,24.1,24.2,24.1
XS GIS Cut Line= 3
     1793844.255      445341.304     1793832.276      445282.971
      1793825.54       445159.62
#Sta/Elev= 23
       0  696.66     8.5  692.09      17  691.18    25.5  687.27    26.2  687.05
      34  684.64    41.2  684.34    42.5  684.29      51  686.13    59.6  688.79
      69  690.18    78.6  690.57    88.1  690.76    97.6  691.04   107.1  691.27
   116.6  691.48   126.1  691.69   135.6  691.98   145.1  692.18   154.6  692.48
   164.1  692.91   173.6  693.59   183.1  694.38
#Mann= 3 , 0 , 0
       0     .06       0    26.2    .045       0      51     .06       0
Bank Sta=26.2,51
XS Rating Curve= 0 ,0
Exp/Cntr=0.3,0.1

Type RM Length L Ch R = 1 ,772.5   ,10.7,10.4,14
XS GIS Cut Line= 3
     1793867.692      445337.138     1793855.713      445278.804
     1793849.845       445153.37
#Sta/Elev= 23
       0  693.68     8.5  691.23      17  689.24    22.5  687.43    25.5  686.44
      34     684    37.5  684.19    42.5  684.47      51  687.27    59.6  689.14
    69.2  689.95    78.9  690.12    88.5  690.23    98.2   690.4   107.8  690.62
   117.5  690.86   127.2  691.04   136.8  691.23   146.5  691.38   156.1   691.5
   165.8  691.76   175.5  692.33   185.1  693.23
#Mann= 3 , 0 , 0
       0     .06       0    22.5    .045       0    42.5     .06       0
Bank Sta=22.5,42.5
XS Rating Curve= 0 ,0
Exp/Cntr=0.3,0.1

Type RM Length L Ch R = 1 ,762.1   ,11.7,11.9,9.1
XS GIS Cut Line= 4
      1793878.63      445335.054      1793872.38      445314.221
     1793868.213       445232.45     1793863.526      445186.096
#Sta/Elev= 21
       0  692.34     7.2  690.93    14.5  689.41    21.4  687.49    21.8  687.38
    30.8  684.46    36.4  684.07      40  683.82   41.67  684.36      49  686.83
    58.1  688.95    67.2   689.8    76.3  690.03    85.4  690.07    94.5  690.12
   103.6  690.26     113  690.44   122.3  690.57   131.6  690.68   140.9  690.77
   150.2  690.89
#Mann= 3 , 0 , 0
       0     .06       0    21.8    .045       0   41.67     .06       0
Bank Sta=21.8,41.67
XS Rating Curve= 0 ,0
Exp/Cntr=0.3,0.1

Type RM Length L Ch R = 1 ,750.2   ,20.5,20.5,20.4
XS GIS Cut Line= 3
     1793890.088      445336.617     1793880.192      445288.179
     1793874.984      445177.242
#Sta/Elev= 22
       0  692.87     8.2  690.75    16.5  689.38    23.9   687.6    24.7  687.41
      33  684.62    38.9  684.04    41.2  683.81   43.37  684.45    49.4  686.08
    58.7  688.47      68   689.6    77.2  689.87    86.5  689.88    95.7  689.93
     105  690.03   114.2  690.14   123.5  690.25   132.7  690.34     142  690.36
   151.2  690.47   160.5   690.7
#Mann= 3 , 0 , 0
       0     .06       0    24.7    .045       0   43.37     .06       0
Bank Sta=24.7,43.37
XS Rating Curve= 0 ,0
Exp/Cntr=0.3,0.1

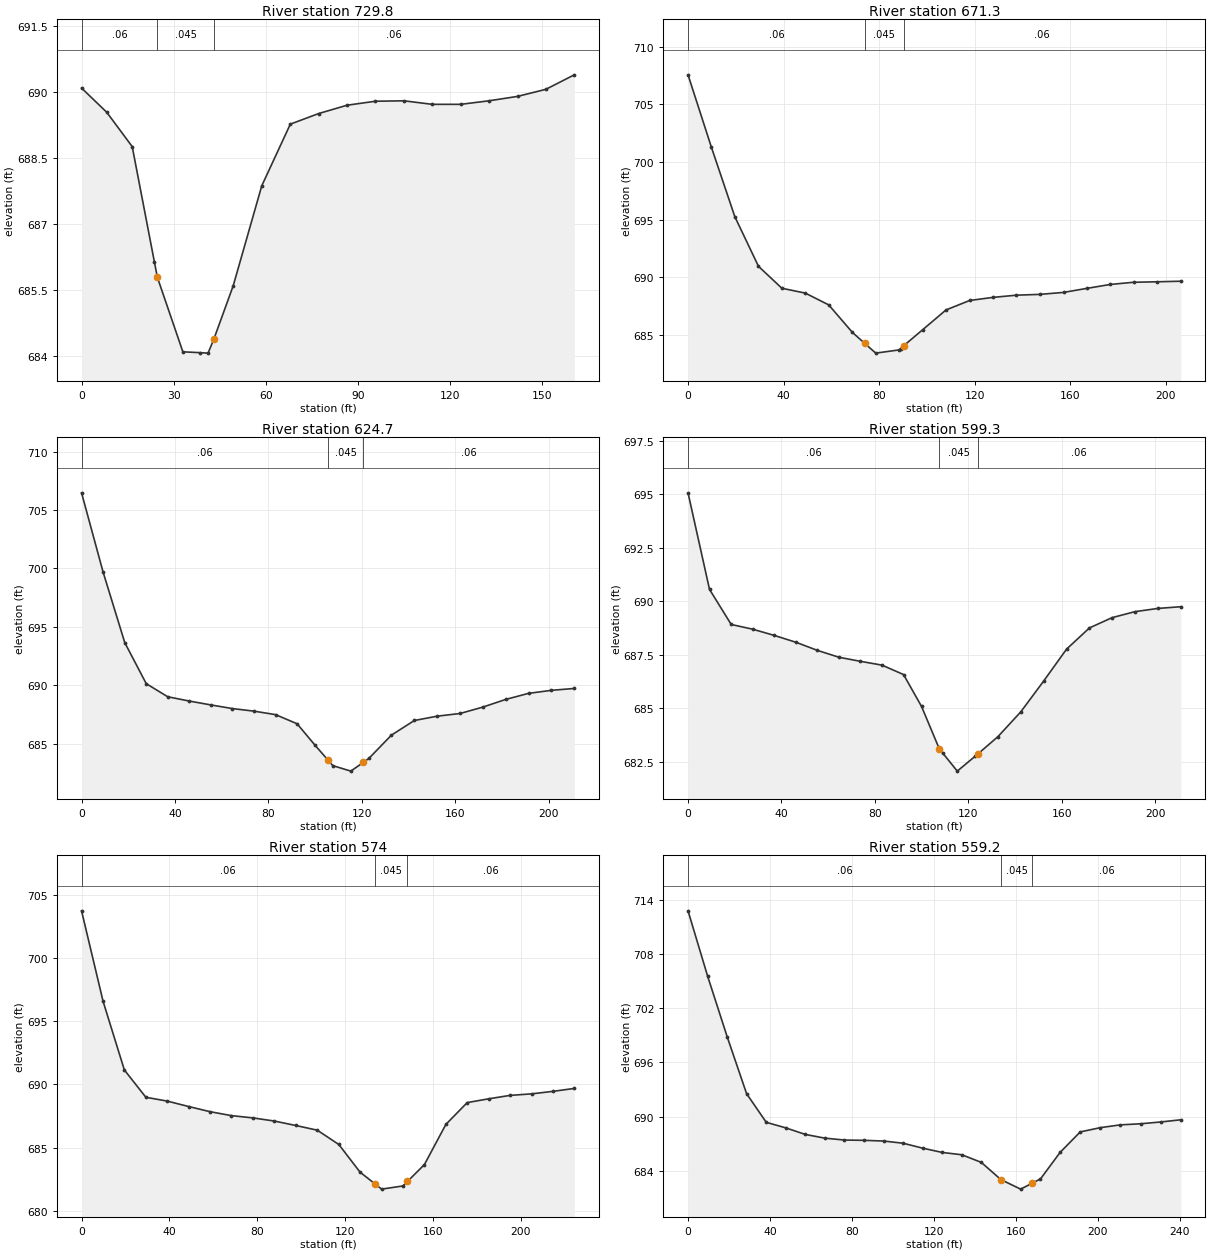
Type RM Length L Ch R = 1 ,729.8   ,52.6,58.5,66.1
XS GIS Cut Line= 3
      1793909.88      445331.409     1793899.984      445282.971
     1793894.776      445172.034
#Sta/Elev= 22
       0  690.09     8.2  689.54    16.5  688.76    23.7  686.15    24.7  685.79
      33   684.1    38.7  684.08    41.2  684.07   43.05  684.38    49.4   685.6
    58.7  687.87      68  689.27    77.2  689.51    86.5   689.7    95.7  689.79
     105   689.8   114.2  689.72   123.5  689.72   132.7   689.8     142   689.9
   151.2  690.06   160.5  690.39
#Mann= 3 , 0 , 0
       0     .06       0    24.7    .045       0   43.05     .06       0
Bank Sta=24.7,43.05
XS Rating Curve= 0 ,0
Exp/Cntr=0.3,0.1

Type RM Length L Ch R = 1 ,671.3   ,59,46.6,39.1
XS GIS Cut Line= 2
     1793956.755      445357.971     1793954.151      445151.721
#Sta/Elev= 25
       0  707.55     9.8  701.27    19.6  695.26    29.5  690.96    39.3  689.06
    49.1  688.64    58.9  687.62    68.8  685.24      74  684.28    78.6  683.44
    88.4  683.72      89  683.83   90.35  684.09    98.2  685.46     108  687.18
   117.9     688   127.7  688.27   137.5  688.46   147.3  688.53   157.2   688.7
     167  689.05   176.8  689.39   186.6  689.58   196.4  689.62   206.3  689.67
#Mann= 3 , 0 , 0
       0     .06       0      74    .045       0   90.35     .06       0
Bank Sta=74,90.35
XS Rating Curve= 0 ,0
Exp/Cntr=0.3,0.1

Type RM Length L Ch R = 1 ,624.7   ,24.6,25.4,26.6
XS GIS Cut Line= 4
     1793995.817      445354.846     1794000.505      445262.659
     1793984.359      445236.617     1793981.755      445148.596
#Sta/Elev= 26
       0  706.47     9.2  699.71    18.5  693.66    27.7  690.15    36.9  689.03
    46.2  688.66    55.4  688.33    64.6  688.02    73.8   687.8    83.1   687.5
    92.3  686.72     100  684.88   105.6   683.6   107.6  683.14   115.3  682.67
   120.6  683.41     123  683.75   132.7  685.75   142.5     687   152.3  687.37
   162.1   687.6   171.9  688.15   181.6   688.8   191.4  689.32   201.2  689.58
     211  689.74
#Mann= 3 , 0 , 0
       0     .06       0   105.6    .045       0   120.6     .06       0
Bank Sta=105.6,120.6
XS Rating Curve= 0 ,0
Exp/Cntr=0.3,0.1

Type RM Length L Ch R = 1 ,599.3   ,12.4,25.3,27.4
XS GIS Cut Line= 4
     1794014.047        445338.7     1794018.734      445246.513
     1794002.588      445220.471     1793999.984       445132.45
#Sta/Elev= 26
       0  695.06     9.2  690.55    18.5  688.91    27.7  688.69    36.9   688.4
    46.2  688.08    55.4   687.7    64.6  687.38    73.8  687.19    83.1  687.01
    92.3  686.57     100  685.08   107.6   683.1   109.1   682.9   115.3  682.06
     123  682.76   124.1  682.86   132.7  683.67   142.5  684.83   152.3  686.27
   162.1  687.76   171.9  688.75   181.6  689.23   191.4  689.51   201.2  689.66
     211  689.74
#Mann= 3 , 0 , 0
       0     .06       0   107.6    .045       0   124.1     .06       0
Bank Sta=107.6,124.1
XS Rating Curve= 0 ,0
Exp/Cntr=0.3,0.1

Type RM Length L Ch R = 1 ,574     ,24.4,14.8,5.7
XS GIS Cut Line= 2
      1794028.63      445350.679     1794023.422        445126.2
#Sta/Elev= 26
       0  703.72     9.8  696.57    19.5  691.14    29.3  688.98      39  688.68
    48.8  688.25    58.6  687.84    68.3  687.53    78.1  687.35    87.9   687.1
    97.6  686.75   107.4  686.38   117.2  685.25   126.9  683.06   133.5  682.16
   136.7  681.72   146.4  681.97   148.5  682.33   156.2  683.66     166  686.84
   175.7  688.56   185.5  688.86   195.2  689.13     205  689.25   214.8  689.45
   224.5  689.68
#Mann= 3 , 0 , 0
       0     .06       0   133.5    .045       0   148.5     .06       0
Bank Sta=133.5,148.5
XS Rating Curve= 0 ,0
Exp/Cntr=0.3,0.1

Type RM Length L Ch R = 1 ,559.2   ,22.7,24.9,24.4
XS GIS Cut Line= 4
     1794046.338      445363.179     1794046.338       445219.95
     1794030.192      445185.054     1794027.588        445126.2
#Sta/Elev= 28
       0  712.76     9.6  705.51    19.1  698.84    28.6  692.53    38.2  689.36
    47.7  688.75    57.3  688.02    66.8  687.61    76.4   687.4    85.9  687.37
    95.5  687.29     105  687.05   114.6   686.5   124.1  686.03   133.7  685.77
   143.2  684.93   152.8  683.02     153     683   162.4  681.97     168  682.62
   172.1   683.1   181.7  686.04   191.5   688.3   201.3  688.77   211.1  689.08
     221   689.2   230.8   689.4   240.6  689.64
#Mann= 3 , 0 , 0
       0     .06       0     153    .045       0     168     .06       0
Bank Sta=153,168
XS Rating Curve= 0 ,0
Exp/Cntr=0.3,0.1

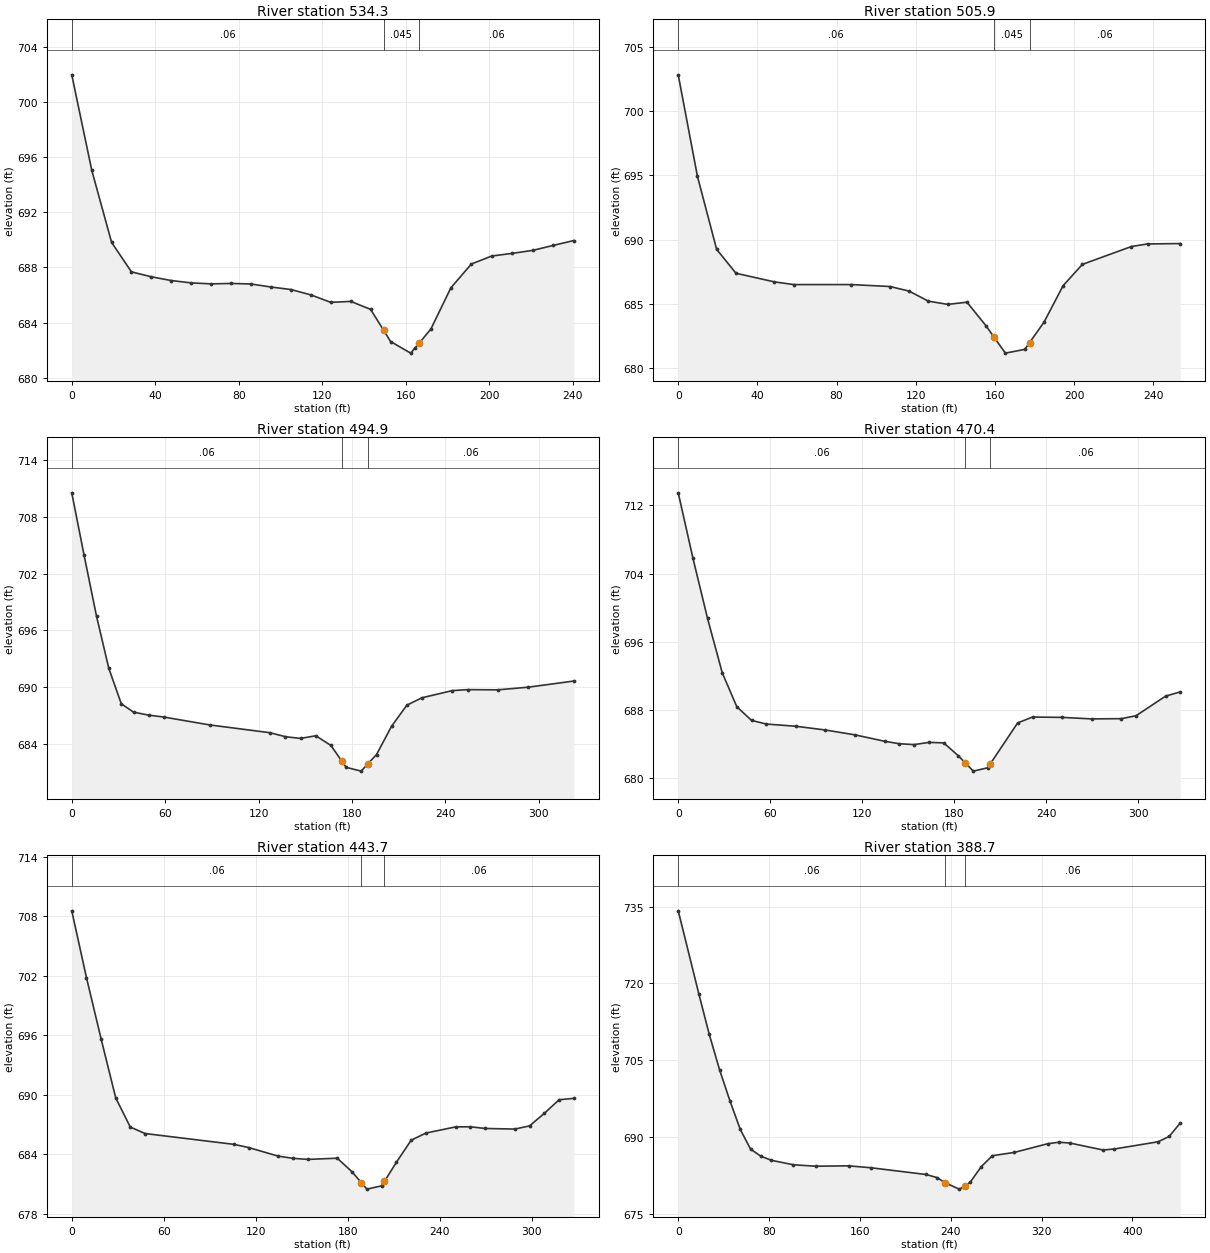
Type RM Length L Ch R = 1 ,534.3   ,22,28.4,38.6
XS GIS Cut Line= 4
     1794067.692      445350.159     1794067.692      445206.929
     1794051.547      445172.034     1794048.942      445113.179
#Sta/Elev= 29
       0  701.96     9.6  695.03    19.1  689.81    28.6  687.68    38.2  687.32
    47.7  687.05    57.3  686.88    66.8  686.81    76.4  686.84    85.9   686.8
    95.5  686.58     105   686.4   114.6  686.01   124.1  685.47   133.7  685.54
   143.2  684.96   149.4  683.46   152.8  682.63   162.4  681.79   164.4  682.15
  166.52  682.52   172.1  683.54   181.7  686.53   191.5  688.25   201.3  688.83
   211.1  689.02     221  689.24   230.8   689.6   240.6  689.95
#Mann= 3 , 0 , 0
       0     .06       0   149.4    .045       0  166.52     .06       0
Bank Sta=149.4,166.52
XS Rating Curve= 0 ,0
Exp/Cntr=0.3,0.1

Type RM Length L Ch R = 1 ,505.9   ,12.4,11,9.9
XS GIS Cut Line= 3
     1794084.359      445353.284     1794090.088      445149.117
     1794090.088      445099.638
#Sta/Elev= 23
       0  702.81     9.7  694.92    19.4  689.24    29.2  687.38    48.6  686.71
    58.4   686.5    87.5   686.5     107  686.35   116.7  685.99   126.4  685.21
   136.2  684.96   145.9  685.13   155.6  683.28   159.4  682.45   165.3  681.17
   175.1  681.46   177.5  681.98   184.8  683.57   194.5  686.42   204.2  688.07
     229  689.46   237.2  689.66   253.7  689.69
#Mann= 3 , 0 , 0
       0     .06       0   159.4    .045       0   177.5     .06       0
Bank Sta=159.4,177.5
XS Rating Curve= 0 ,0
Exp/Cntr=0.3,0.1

Type RM Length L Ch R = 1 ,494.9   ,24.2,24.5,24.5
XS GIS Cut Line= 3
     1794091.651      445364.221     1794103.109        445326.2
     1794096.859      445043.388
#Sta/Elev= 27
       0  710.56     7.9  703.97    15.9  697.51    23.8  691.99    31.8  688.25
    39.7  687.36    49.5  687.04    59.2  686.84    88.5  686.01   127.5  685.18
   137.3  684.76     147  684.58   156.8  684.86   166.5  683.84   173.5  682.18
   176.3  681.52     186  681.12  190.35  681.92   195.8  682.87   205.5  685.87
   215.3   688.1     225  688.88   244.6  689.64   254.3  689.74   273.8  689.72
   293.3     690   322.6  690.65
#Mann= 3 , 0 , 0
       0     .06       0   173.5    .045       0  190.35     .06       0
Bank Sta=173.5,190.35
XS Rating Curve= 0 ,0
Exp/Cntr=0.3,0.1

Type RM Length L Ch R = 1 ,470.4   ,26.8,26.7,26.7
XS GIS Cut Line= 3
     1794107.276      445370.992     1794126.547      445327.242
     1794121.859      445047.554
#Sta/Elev= 28
       0  713.47     9.6   705.8    19.1  698.76    28.7  692.38    38.2   688.4
    47.8   686.8    57.4  686.37    76.7  686.11      96  685.67   115.3   685.1
   134.6  684.35   144.3  684.06   153.9  683.96   163.6  684.22   173.2  684.16
   182.8  682.63     187  681.86   192.5  680.85     202  681.25  203.68  681.74
   221.4   686.5   231.1  687.19   250.4  687.15   269.7  686.97     289     687
   298.6  687.34   317.9  689.64   327.5  690.14
#Mann= 3 , 0 , 0
       0     .06       0     187    .045       0  203.68     .06       0
Bank Sta=187,203.68
XS Rating Curve= 0 ,0
Exp/Cntr=0.3,0.1

Type RM Length L Ch R = 1 ,443.7   ,54.3,55,55.7
XS GIS Cut Line= 3
     1794133.838      445370.471     1794153.109      445326.721
     1794148.422      445047.034
#Sta/Elev= 28
       0  708.54     9.6  701.79    19.1  695.64    28.7  689.65    38.2  686.72
    47.8  686.07   105.7  684.98   115.3  684.66   134.6  683.79   144.3  683.57
   153.9  683.46   173.2  683.58   182.8  682.21   188.9  681.11   192.5  680.46
   202.1  680.79   203.9  681.23   211.8  683.18   221.4   685.4   231.1  686.12
   250.4  686.74     260  686.75   269.7  686.58     289  686.52   298.6  686.84
   308.2   688.1   317.9  689.48   327.5  689.62
#Mann= 3 , 0 , 0
       0     .06       0   188.9    .045       0   203.9     .06       0
Bank Sta=188.9,203.9
XS Rating Curve= 0 ,0
Exp/Cntr=0.3,0.1

Type RM Length L Ch R = 1 ,388.7   ,90.6,91.7,92.7
XS GIS Cut Line= 3
     1794167.692      445411.964     1794203.283      445338.179
     1794208.491      444977.936
#Sta/Elev= 30
       0  734.17    18.2  717.89    27.3  710.05    36.4  703.12    45.5  697.07
    54.6  691.48    63.7  687.62    72.8  686.23    81.9  685.44   101.4  684.56
   120.9  684.28   150.1  684.35   169.6  683.98   218.2  682.66     228  682.05
   234.7  681.09   247.4   679.8  252.44  680.36   257.2  681.16   266.9   684.2
   276.7  686.33   296.1  686.98   325.4  688.67   335.1  688.96   344.8  688.81
     374  687.45   383.8  687.63   422.7  689.05   432.5  690.11   442.2  692.74
#Mann= 3 , 0 , 0
       0     .06       0   234.7    .045       0  252.44     .06       0
Bank Sta=234.7,252.44
XS Rating Curve= 0 ,0
Exp/Cntr=0.3,0.1

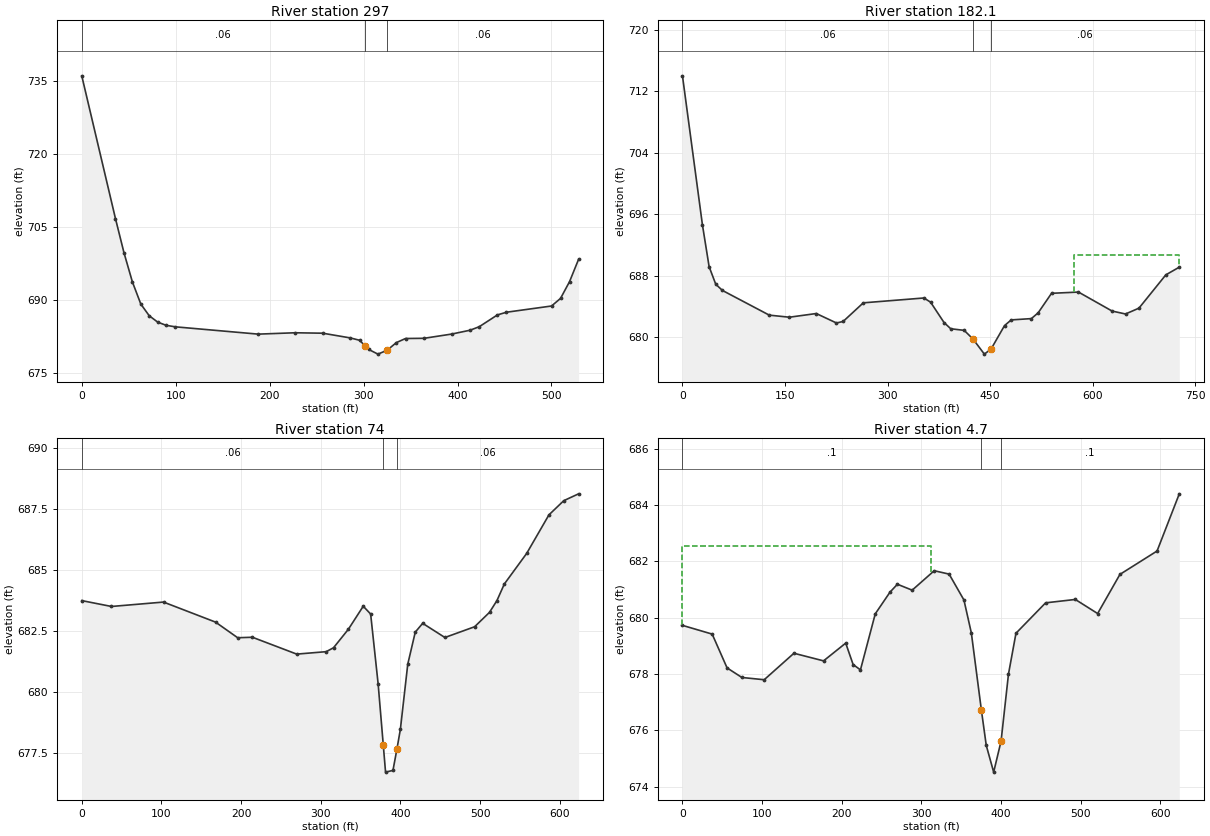
Type RM Length L Ch R = 1 ,297     ,116.3,114.9,113.5
XS GIS Cut Line= 4
     1794235.401      445448.422     1794286.616      445374.638
     1794298.769      445031.756     1794259.706      444944.082
#Sta/Elev= 30
       0  736.09    35.9  706.74    44.9  699.77    53.9  693.74    62.9  689.18
    71.8  686.79    80.8  685.48    89.8  684.82    99.6  684.51   187.8  683.01
   227.1  683.29   256.5   683.2   285.9  682.23   295.7  681.75   301.3  680.67
   305.5  679.86   315.3   678.9   325.1   679.7   334.9  681.27   344.7  682.11
   364.3  682.15   393.7  683.02   413.3  683.81   423.1  684.53   442.5  686.96
   452.1  687.51   500.1  688.79   509.7  690.36   519.3  693.81   528.9  698.39
#Mann= 3 , 0 , 0
       0     .06       0   301.3    .045       0   325.1     .06       0
Bank Sta=301.3,325.1
XS Rating Curve= 0 ,0
Exp/Cntr=0.3,0.1

Type RM Length L Ch R = 1 ,182.1   ,107.6,108.1,107.8
XS GIS Cut Line= 3
     1794363.005       445534.36     1794407.276      445447.554
     1794395.123      444818.214
#Sta/Elev= 30
       0  714.02    29.2  694.65      39   689.2    48.7  686.92    58.5  686.11
     127   682.9   156.4  682.63   195.8  683.11   225.3  681.88   235.1  682.08
   264.6   684.5   353.2  685.13     363  684.59   382.7  681.94   392.5  681.13
   412.2  680.92   425.1  679.79   441.7  677.83   451.5  678.49   471.2  681.54
     481  682.28   510.5  682.45   520.4   683.2     540  685.74   579.4   685.9
   628.6  683.43   648.2  683.05   667.9  683.81   707.2  688.14   726.9  689.14
#Mann= 3 , 0 , 0
       0     .06       0   425.1    .045       0   451.5     .06       0
#XS Ineff= 2 , 0
                          572.54          690.71
Permanent Ineff=
       F       F
Bank Sta=425.1,451.5
XS Rating Curve= 0 ,0
Exp/Cntr=0.3,0.1

Type RM Length L Ch R = 1 ,74      ,69.8,69.3,69.2
XS GIS Cut Line= 5
     1794554.845       445444.95     1794519.255      445280.888
     1794498.422      445134.186     1794496.685      444994.429
     1794522.727      444828.631
#Sta/Elev= 30
       0  683.74    37.3   683.5   102.6  683.68   167.9  682.86   195.7  682.22
   214.2  682.24   269.8  681.55   306.8  681.65     316  681.81   334.7  682.57
   353.3  683.51   362.6  683.19     372  680.33   378.4  677.85   381.3  676.72
   390.6  676.79  395.57  677.66   399.9  678.47   409.2  681.14   418.6  682.45
   427.9  682.81   455.8  682.23   493.1  682.67   511.8  683.26   521.1  683.74
   530.4  684.42   558.4  685.67   586.4  687.25     605  687.83   623.6  688.11
#Mann= 3 , 0 , 0
       0     .06       0   378.4    .045       0  395.57     .06       0
Bank Sta=378.4,395.57
XS Rating Curve= 0 ,0
Exp/Cntr=0.3,0.1

Type RM Length L Ch R = 1 ,4.7     ,2.4,4.7,6.9
XS GIS Cut Line= 5
     1794623.422      445438.874     1794587.831      445274.811
     1794566.998       445128.11     1794565.262      444988.353
     1794591.303      444822.554
#Sta/Elev= 30
       0  679.73    37.3  679.42      56  678.22    74.6  677.88   102.6   677.8
   139.9  678.74   177.1  678.47   204.9   679.1   214.2  678.34   223.4  678.15
     242  680.14   260.5  680.91   269.8  681.19   288.3  680.98     316  681.67
   334.7  681.55   353.3  680.63   362.6  679.46   375.1  676.74   381.3  675.47
   390.6  674.52   399.9  675.62   409.2     678   418.6  679.45   455.8  680.53
   493.1  680.65   521.1  680.15   549.1  681.54   595.7  682.37   623.6   684.4
#Mann= 3 , 0 , 0
       0      .1       0   375.1    .045       0   399.9      .1       0
#XS Ineff= 2 , 0
          311.87  682.56
Permanent Ineff=
       F       F
Bank Sta=375.1,399.9
XS Rating Curve= 0 ,0
Exp/Cntr=0.3,0.1

Chan Stop Cuts=-1
Use User Specified Reach Order=0
Composite Channel Slope=5